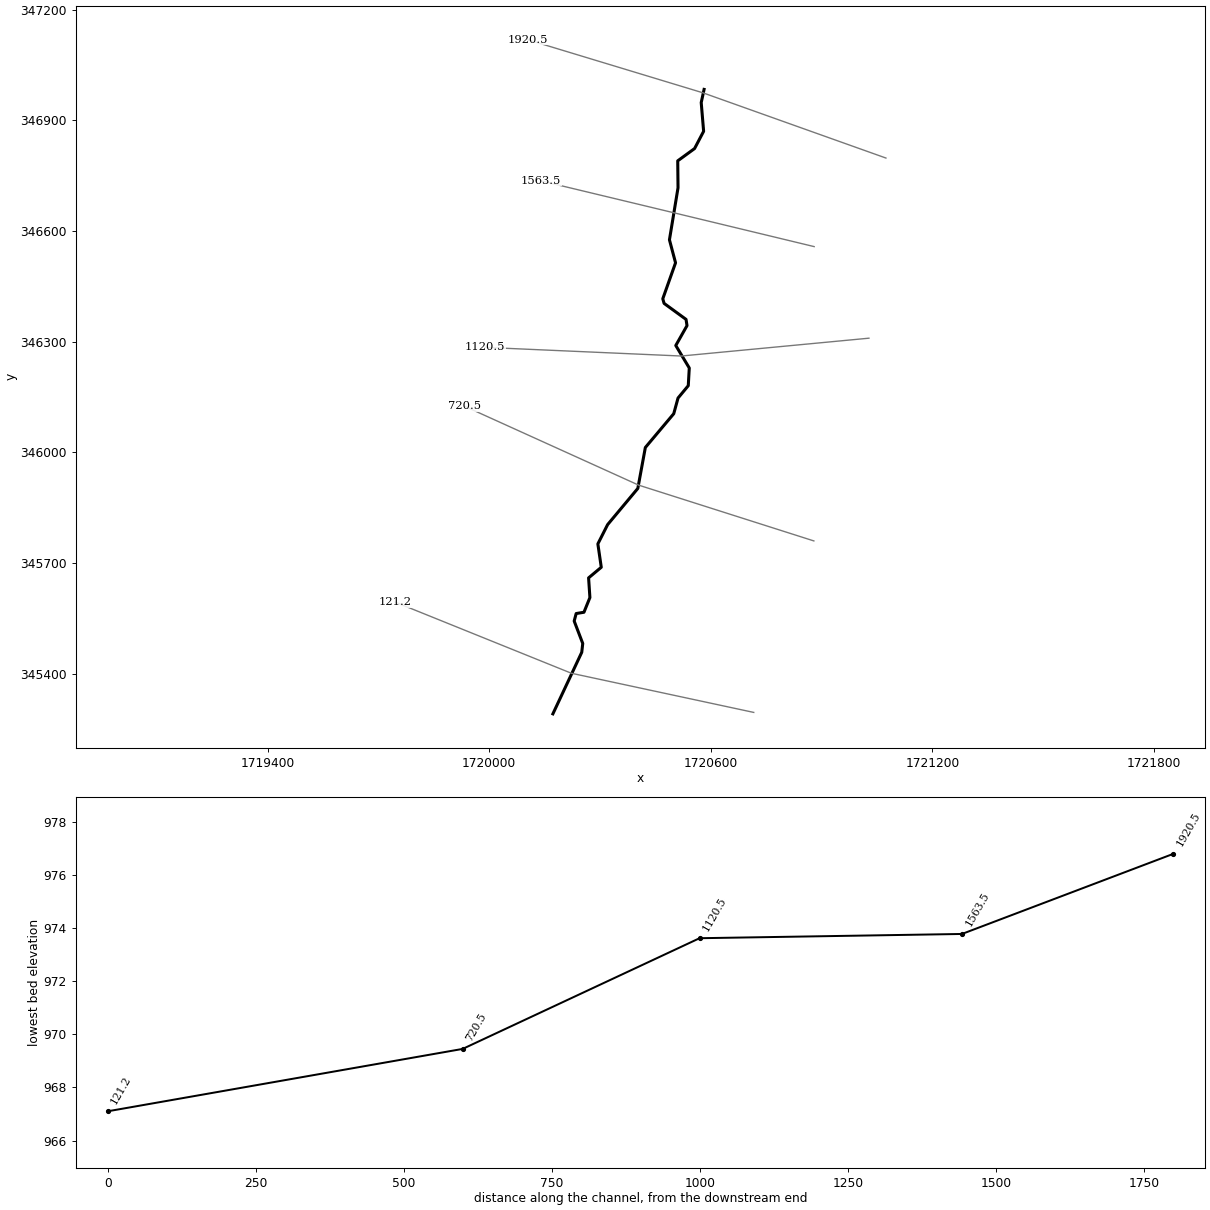
--- BigRn.prj (project) ---

Proj Title=BigRn
Current Plan=p01
Geom File=g01
Flow File=f01
Plan File=p01
DSS Export Rating Curves=0
DSS Export Rating Curve Sorted=0
DSS Export Volume Flow Curves=0
DXF OffsetX=0
DXF OffsetY=0
DXF ScaleX=0
DXF ScaleY=0

--- BigRn.p01 (plan) ---

Plan Title=Floodplain
Program Version=4.00
Geom File=g01
Flow File=f01
K Sum by GR=0
Std Step Tol=0.01
Critical Tol=0.01
Num of Std Step Trials=20
Max Error Tol=0.3
Flow Tol Ratio=0.001
Split Flow NTrial=30
Split Flow Tol=0.02
Split Flow Ratio=0.02
Log Output Level=0
Friction Slope Method=1
Unsteady Friction Slope Method=2
Unsteady Bridges Friction Slope Method=1
Global Log Level=0
CheckData=False
Run HTab=0
Run UNet=0
Run PostProcess=0
UNET Theta=0
UNET Theta Warmup=0
UNET ZTol=0
UNET ZSATol=0
UNET MxIter=0
UNET MaxInSteps=0
UNET DtIC=0
UNET DtMin=0
UNET MaxCRTS=0
UNET WFStab=0
UNET SFStab=0
UNET WFX=0
UNET SFX=0
UNET DSS MLevel=0
UNET DZMax Abort=0
UNET Convert EG Bridges=0
UNET Use Existing IB Tables=0
UNET Froude Limit=0
UNET Froude Power=0
Write IC File=0
Echo Input=False
Echo Output=False
Write Detailed=0

--- BigRn.f01 (steady flow) ---

Flow Title=NFF Regression Equation
Program Version=4.00
Number of Profiles=1
Profile Names=P100yr
River Rch & RM=BigRn,Main      ,1920.5
1443.448
River Rch & RM=BigRn,Main      ,121.2
1469.992
Boundary for River Rch & Prof#=BigRn,Main      ,1
Up Type=0
Dn Type=3
Dn Slope=0.0048

--- BigRn.g01 (geometry) ---

Geom Title=USGS 3m DEM
Program Version=4.00

River Reach=BigRn     ,Main
Reach XY= 30
     1720581.743      346983.658     1720573.980      346947.947
     1720580.514      346870.093     1720555.977      346823.269
     1720510.411      346790.011     1720511.208      346717.029
     1720487.974      346575.978     1720504.492      346513.580
     1720469.941      346416.073     1720473.500      346403.578
     1720532.874      346360.245     1720535.536      346343.314
     1720505.134      346289.436     1720541.665      346228.509
     1720538.942      346180.514     1720511.247      346147.062
     1720499.598      346104.520     1720422.753      346012.985
     1720402.349      345901.993     1720320.644      345803.968
     1720294.184      345751.687     1720303.409      345688.288
     1720269.110      345659.541     1720272.647      345606.159
     1720256.546      345566.356     1720235.464      345562.879
     1720230.093      345542.496     1720253.263      345481.755
     1720250.568      345457.782     1720172.437      345290.929

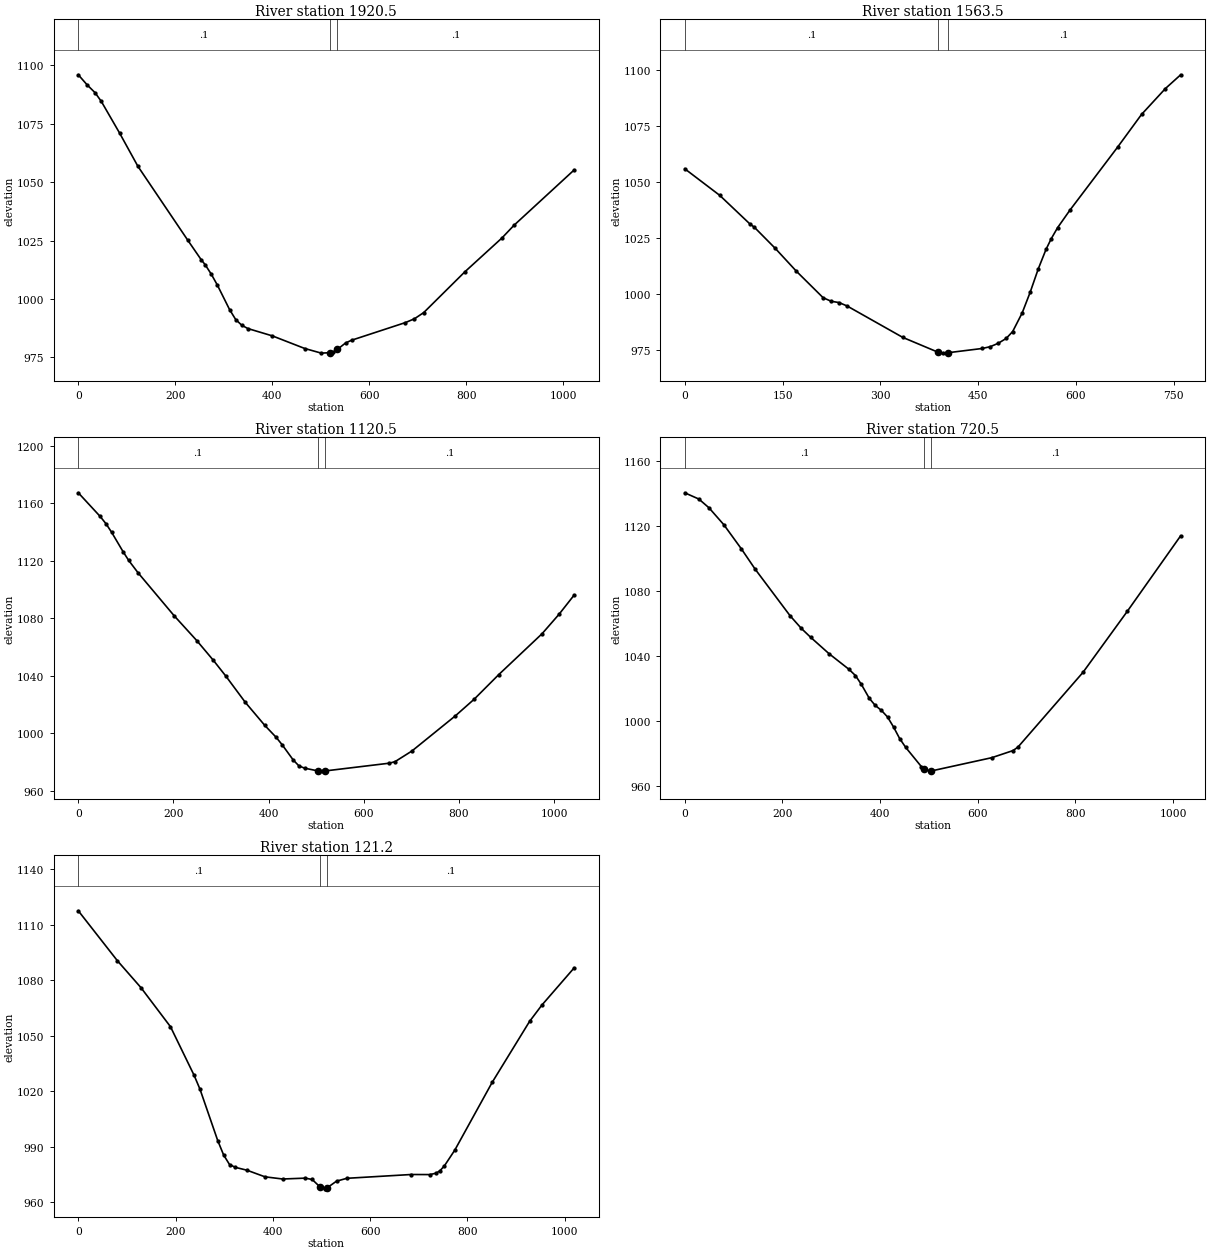
Type RM Length L Ch R = 1 ,1920.5,353.766,357.003,359.163
XS GIS Cut Line= 3
     1721074.045      346797.586     1720577.986      346974.603
     1720103.479      347118.544
#Sta/Elev= 30
       0 1095.98    18.5 1091.60    34.6 1088.31    47.2 1084.66    85.0 1071.07
   122.8 1056.82   225.5 1025.21   253.3 1016.82   261.5 1014.68   274.1 1010.64
   286.7 1005.94   311.9  995.45   324.5  991.19   336.9  988.76   349.7  987.32
   400.2  984.18   467.0  978.78   501.0  976.80   519.2  976.99   526.2  977.19
   534.2  978.40   551.0  981.13   563.4  982.32   674.5  989.88   693.2  991.52
   712.3  994.17   797.2 1011.64   873.6 1026.11   898.4 1031.54  1022.5 1055.25
#Mann= 3 , 0 , 0
       0     0.1       0   519.2   0.045       0   534.2     0.1       0
Bank Sta=   519.2,   534.2
Exp/Cntr=0.3,0.1

Type RM Length L Ch R = 1 ,1563.5,434.984,442.997,444.867
XS GIS Cut Line= 3
     1720879.729      346557.523     1720492.148      346651.077
     1720140.206      346735.721
#Sta/Elev= 30
       0 1055.89    53.5 1044.09    99.6 1031.40   106.8 1029.83   138.8 1020.44
   171.2 1010.26   212.2  998.47   224.5  996.89   236.7  996.30   248.9  994.80
   334.4  980.79   388.5  974.19   395.4  973.78   403.5  973.95   456.5  975.86
   468.7  976.66   480.9  978.17   493.1  980.33   503.0  983.39   517.6  991.68
   529.8 1000.84   542.4 1011.39   554.2 1020.00   562.1 1024.70   571.9 1029.65
   590.8 1037.45   664.1 1065.58   700.7 1080.10   737.4 1091.66   760.7 1097.76
#Mann= 3 , 0 , 0
       0     0.1       0   388.5   0.045       0   403.5     0.1       0
Bank Sta=   388.5,   403.5
Exp/Cntr=0.3,0.1

Type RM Length L Ch R = 1 ,1120.5,408.435,400,394.187
XS GIS Cut Line= 3
     1721028.066      346309.280     1720519.928      346260.918
     1719988.538      346284.389
#Sta/Elev= 30
       0 1167.28    45.9 1150.84    58.1 1145.79    70.0 1139.82    93.9 1126.41
   105.8 1120.28   125.5 1111.66   201.2 1081.83   248.9 1064.49   283.7 1050.79
   310.1 1039.74   350.9 1021.53   392.0 1005.43   415.9  997.13   428.7  991.87
   451.7  981.39   463.6  977.31   475.5  975.68   502.9  973.84   514.7  973.62
   517.9  973.72   653.9  979.15   665.8  980.23   701.2  987.61   792.7 1012.12
   832.2 1023.69   883.7 1040.76   974.8 1069.22  1010.4 1082.72  1042.3 1096.13
#Mann= 3 , 0 , 0
       0     0.1       0   502.9   0.045       0   517.9     0.1       0
Bank Sta=   502.9,   517.9
Exp/Cntr=0.3,0.1

Type RM Length L Ch R = 1 ,720.5,590.778,599.314,598.547
XS GIS Cut Line= 3
     1720878.968      345759.717     1720404.854      345910.844
     1719933.445      346124.721
#Sta/Elev= 30
       0 1140.64    28.8 1136.81    49.6 1131.41    80.0 1121.00   116.1 1106.06
   144.1 1093.67   215.7 1064.98   238.6 1057.25   257.5 1051.83   295.3 1041.70
   336.1 1032.09   349.5 1028.22   361.5 1022.83   377.7 1014.28   389.8 1009.91
   402.7 1006.78   415.1 1002.77   427.6  996.52   440.0  989.46   452.5  983.99
   484.3  972.27   490.1  970.60   502.6  969.45   505.1  969.58   628.5  977.71
   672.1  982.09   682.3  984.26   815.5 1030.25   906.0 1067.71  1015.3 1114.17
#Mann= 3 , 0 , 0
       0     0.1       0   490.1   0.045       0   505.1     0.1       0
Bank Sta=   490.1,   505.1
Exp/Cntr=0.3,0.1

Type RM Length L Ch R = 1 ,121.2,126.341,121.216,119.845
XS GIS Cut Line= 3
     1720716.196      345294.846     1720222.506      345401.023
     1719745.418      345593.886
#Sta/Elev= 30
       0 1117.49    80.2 1090.56   128.8 1075.97   189.5 1054.86   238.1 1028.59
   250.2 1021.07   286.6  993.37   298.8  985.54   310.9  980.39   323.1  978.85
   346.8  977.32   383.8  973.75   420.2  972.57   466.7  973.04   480.9  972.31
   496.2  968.48   506.6  967.10   511.2  967.74   530.9  971.40   552.2  972.95
   684.5  975.00   723.0  974.96   735.8  975.73   743.7  977.04   752.8  979.69
   774.2  988.20   851.0 1024.79   927.8 1057.69   953.3 1066.58  1019.6 1086.66
#Mann= 3 , 0 , 0
       0     0.1       0   496.2   0.045       0   511.2     0.1       0
Bank Sta=   496.2,   511.2
Exp/Cntr=0.3,0.1